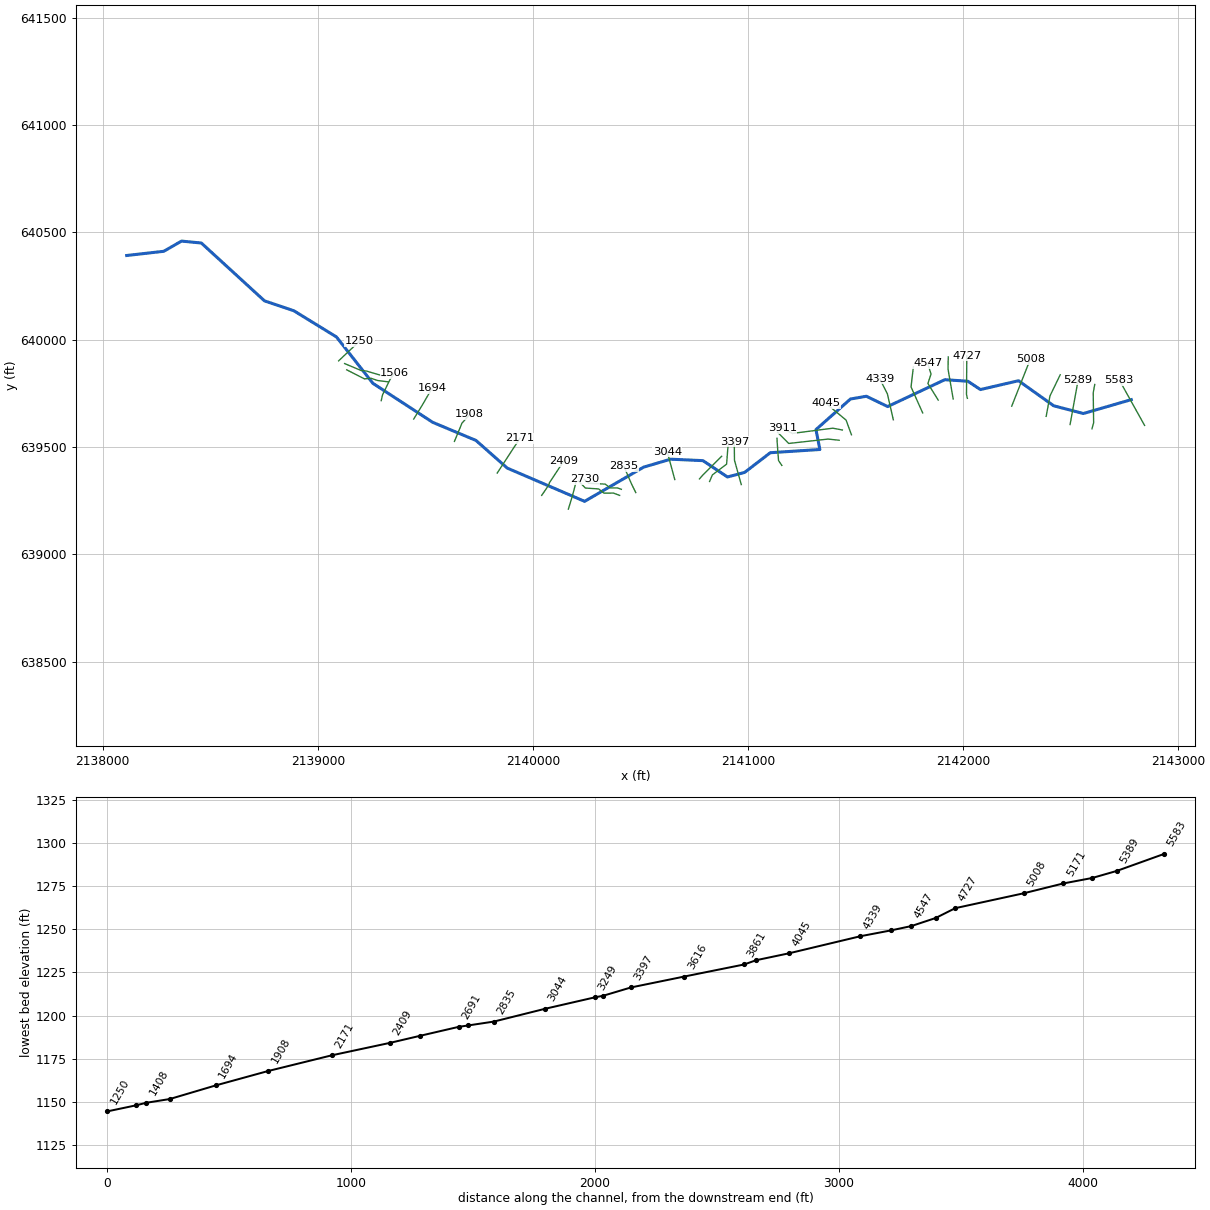
--- TRACERN.prj (project) ---

Proj Title=TRACERN
Current Plan=p01
Default Exp/Contr=0,0
English Units
Geom File=g01
Flow File=f01
Plan File=p01
BEGIN DESCRIPTION:
---------- MODELED AS PART OF WVEMD CTP PROGRAM, 2023----------
Stream Name: Trace Run
Flood Zone:  AFH
Upshur County, WV
HEC-RAS Version: RAS 6.3
Vertical Datum: NAVD88
Projection: NAD 1983 StatePlane West Virginia S FIPS 4702 (US Feet)
Terrain: 1-meter LIDAR (FEMA Region III 3DEP collected 2016-2018)
Land Use: 2019 NLCD
Hydrologic Method:
WV SIR2010-5033 regression equations
Additional Model Notes:
None
END DESCRIPTION:
DSS Export Rating Curves= 0
DSS Export Rating Curve Sorted= 0
DSS Export Volume Flow Curves= 0
DXF OffsetX= 0
DXF OffsetY= 0
DXF ScaleX= 0
DXF ScaleY= 0

--- TRACERN.p01 (plan) ---

Plan Title=Floodplain
Program Version=6.30
Short Identifier=Floodplain
Geom File=g01
Flow File=f01
Subcritical Flow
K Sum by GR= 0
Std Step Tol= 0.01
Critical Tol= 0.01
Num of Std Step Trials= 20
Max Error Tol= 0.3
Flow Tol Ratio= 0.001
Split Flow NTrial= 30
Split Flow Tol= 0.02
Split Flow Ratio= 0.02
Log Output Level= 0
Friction Slope Method= 1
Unsteady Friction Slope Method= 2
Unsteady Bridges Friction Slope Method= 1
Parabolic Critical Depth
Global Vel Dist= 0 , 0 , 0
Global Log Level= 0
CheckData=False
Encroach Param=-1 ,0,0, 0
Mapping Interval=1HOUR
Computation Time Step Use Courant=        0
Computation Time Step Use Time Series=    0
Computation Time Step Count To Double=0
Computation Time Step Max Doubling=0
Computation Time Step Max Halving=0
Computation Time Step Residence Courant=0
Run HTab= 0
Run UNet= 0
Run Sediment= 0
Run PostProcess= 0
Run WQNet= 0
Run RASMapper=-1
UNET Theta= 0
UNET Theta Warmup= 0
UNET ZTol= 0
UNET ZSATol= 0
UNET MxIter= 0
UNET Max Iter WO Improvement= 0
UNET MaxInSteps= 0
UNET DtIC= 0
UNET DtMin= 0
UNET MaxCRTS= 0
UNET WFStab= 0
UNET SFStab= 0
UNET WFX= 1
UNET SFX= 1
UNET Gravity=32.17405
UNET 1D Methodology=Finite Difference
UNET DSS MLevel= 1
UNET Pardiso=0
UNET DZMax Abort= 0
UNET Use Existing IB Tables= 0
UNET Froude Reduction=False
UNET Froude Limit= 0
UNET Froude Power= 0
UNET D1 Cores= 0
UNET WindReference=Eulerian
UNET WindDragFormulation=Hsu (1988)
UNET D2 Coriolis=0
UNET D2 Cores= 0
UNET D2 Theta= 1
UNET D2 Theta Warmup= 1
UNET D2 Z Tol= 0.01
UNET D2 Volume Tol= 0.01
UNET D2 Max Iterations= 20
UNET D2 Equation= 0
UNET D2 RampUpFraction=0.1
UNET D2 TimeSlices= 1
UNET D2 Turbulence Formulation=Non-Conservative (original)
UNET D2 Eddy Viscosity=0.3
UNET D2 Transverse Eddy Viscosity=0.1
UNET D2 Smagorinsky Mixing=0
UNET D2 BCVolumeCheck=0
UNET D2 Cores=0
UNET D2 SolverType=PARDISO (Direct)
UNET D2 Minimum Iterations= 3
UNET D2 Maximum Iterations= 30
UNET D2 Restart Number= 10
UNET D2 Relaxation Coeff=1.3
UNET D2 SOR Precondition Iterations= 10
UNET D2 ILUT Maximum Fill= 8
UNET D2 ILUT Tolerance=1E-08
UNET D2 Convergence Tolerance=0.00001
UNET D1D2 MaxIter= 0
UNET D1D2 ZTol=0.01
UNET D1D2 QTol=0.1
UNET D1D2 MinQTol=1
Write IC File= 0
Write IC File at Fixed DateTime=0
Write IC File at Sim End=0
Echo Input=False
Echo Parameters=False
Echo Output=False
Write Detailed= 0
HDF Write Warmup=0
HDF Write Time Slices=0
HDF Flush=0
HDF Compression= 1
HDF Chunk Size= 1
HDF Spatial Parts= 1
HDF Use Max Rows=0
HDF Fixed Rows= 1
Calibration Method= 0
Calibration Iterations= 20
Calibration Max Change=0.05
Calibration Tolerance=0.2
Calibration Maximum=1.5
Calibration Minimum=0.5
Calibration Optimization Method= 1
WQ AD Non Conservative
WQ ULTIMATE=-1
WQ Max Comp Step=1HOUR
WQ Output Interval=15MIN
WQ Output Selected Increments= 0
WQ Output face flow=0
WQ Output face velocity=0
WQ Output face area=0
WQ Output face dispersion=0
WQ Output cell volume=0
WQ Output cell surface area=0
WQ Output cell continuity=0
WQ Output cumulative cell continuity=0
WQ Output face conc=0
WQ Output face dconc_dx=0
WQ Output face courant=0
WQ Output face peclet=0
WQ Output face adv mass=0
WQ Output face disp mass=0
WQ Output cell mass=0
WQ Output cell source sink temp=0
WQ Output nsm pathways=0
WQ Output nsm derived pathways=0
WQ Create Restart=0
WQ Fixed Restart=0
WQ System Summary=0
WQ Write To DSS=0
Sorting and Armoring Iterations= 10
XS Update Threshold= 0.02
Bed Roughness Predictor= 0
Hydraulics Update Threshold= 0.02
Energy Slope Method= 1
Volume Change Method= 1
Sediment Retention Method= 0
Sediment TS Multiplier= 1
Warm Up Method= 0
XS Weighting Method= 0
Number of US Weighted Cross Sections= 1
Number of DS Weighted Cross Sections= 1
Upstream XS Weight=0
Main XS Weight=1
Downstream XS Weight=0
Number of DS XS's Weighted with US Boundary= 1
Upstream Boundary Weight= 1
Weight of XSs Associated with US Boundary= 0
Number of US XS's Weighted with DS Boundary= 1
Downstream Boundary Weight= 0.5
Weight of XSs Associated with DS Boundary= 0.5
Percentile Method= 0
Sediment Output Level= 3
Mass or Volume Output= 0
Output Increment Type= 1
Profile and TS Output Increment= 1
Transport Output Increment 1
XS Output Flag= 0
XS Output Increment= 10
Read HDF5 Sediment Hotstart= 0
Sediment Hotstart Type= 0
Write Gradation File= 0
Read Gradation Hotstart= 0
Write HDF5 File= 1
Write Binary Output= 1
Write DSS Sediment File= 0
DSS Sediment Output Type= 1
SV Curve= 0
Specific Gage Flag= 0
Subcell Erosion Methods= 0
Subcell Deposition Methods= 0
Advection Scheme= 1
Matrix Solver= 0
Implicit Weighting Factor= 1
Maximum Outer Loop Convergence Iterations= 5
Convergence Maximum Absolute= 0.001
Convergence RMSE= 0.0001
Grain Fractions Max Abs Error= 0.001
Max Subgrid Regions= 1
Max Subgrid Length Scale= 3.402823E+38
Initial Layer Thickness= 3.402823E+38
Min Layer Thickness= 3.402823E+38
Max Layer Thickness= 3.402823E+38
Number of Layers= 5

--- TRACERN.f01 (steady flow) ---

Flow Title=Flows
Program Version=6.30
Number of Profiles= 1
Profile Names=01pct
River Rch & RM=TRACERN,Main,5583
     648
River Rch & RM=TRACERN,Main,3283
     720
River Rch & RM=TRACERN,Main,2171
     804
Boundary for River Rch & Prof#=TRACERN,Main            , 1
Up Type= 0
Dn Type= 3
Dn Slope=0.02
DSS Import GetInterval= 0
DSS Import GetPeak= 0
DSS Import FillOption= 0

--- TRACERN.g01 (geometry) ---

Geom Title=Geometry
Program Version=6.30

River Reach=TRACERN         ,Main
Reach XY= 30
     2142781.439      639721.061     2142558.947      639656.503
     2142420.987      639692.474     2142257.473      639809.229
     2142080.338       639768.05      2142021.96      639806.825
     2141914.821      639814.036     2141648.917      639688.897
     2141550.162      639736.858     2141476.189      639724.066
      2141315.88      639581.728     2141333.851      639488.954
      2141103.46      639473.902     2140984.359      639382.329
     2140904.462      639360.838     2140790.254      639436.987
     2140640.619      639443.769     2140514.735      639406.825
2140240.14716499639247.391257741     2139880.682      639402.218
     2139735.225       639531.02     2139534.052      639615.438
     2139255.929      639797.067      2139086.52      640013.063
2138888.49741702640135.107730087     2138751.765      640181.356
     2138458.362      640450.579     2138366.131      640459.536
      2138283.83       640412.09     2138111.302      640392.459

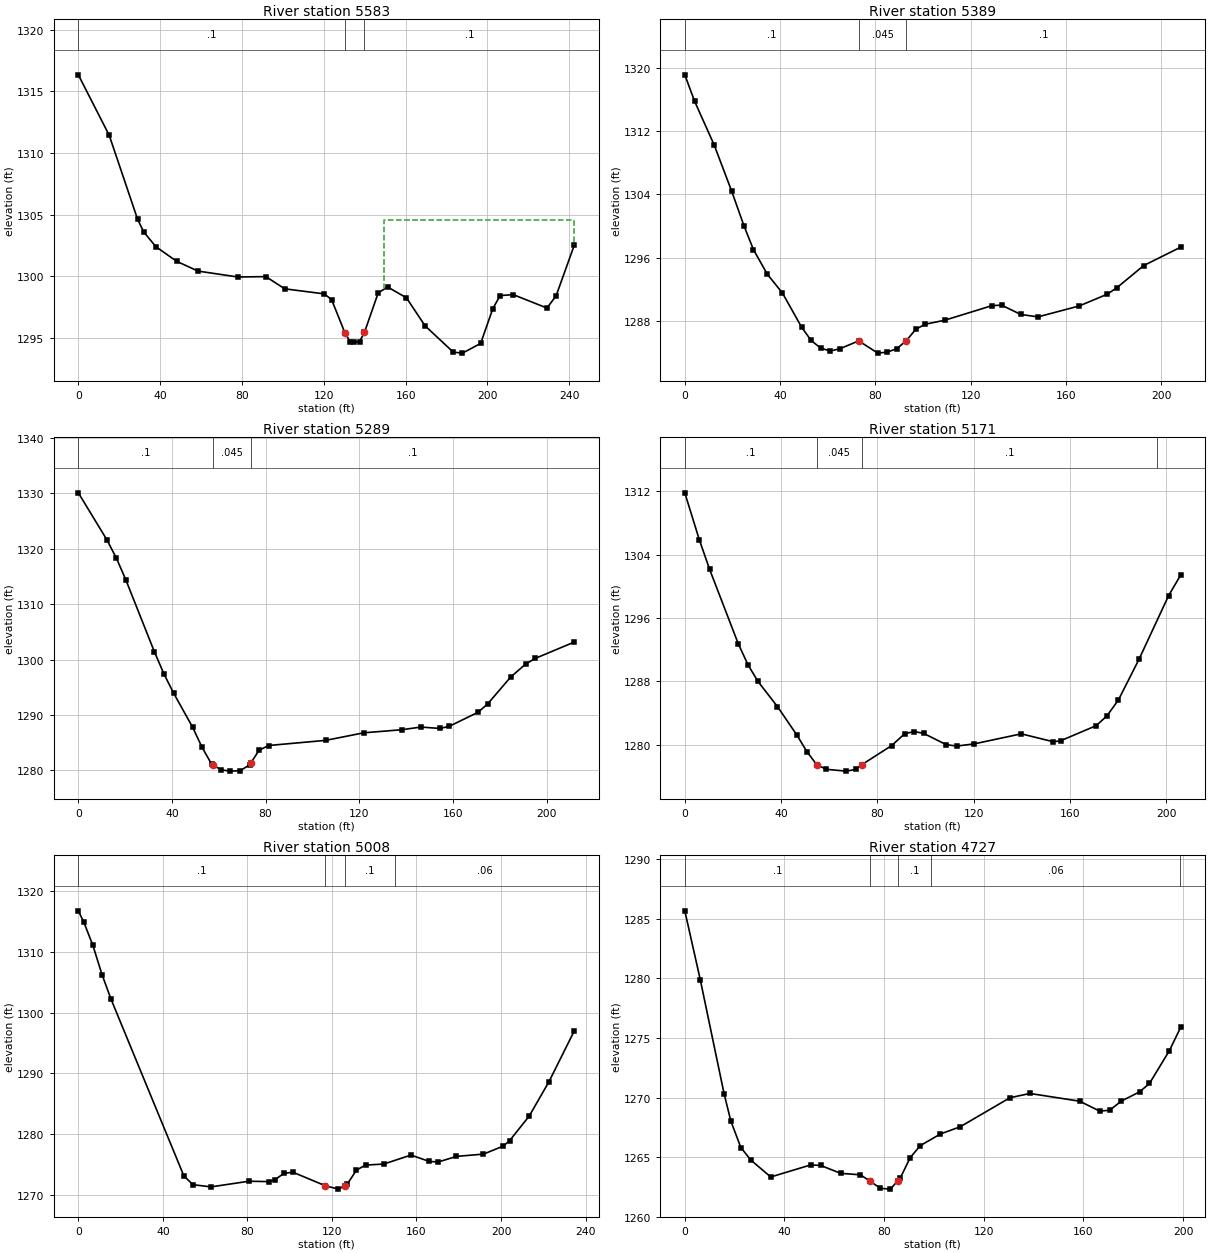
Type RM Length L Ch R = 1 ,5583    ,193.3,193.3,193.3
XS GIS Cut Line= 2
2142843.54141401 639601.041394232142725.66569109639812.851542346
#Sta/Elev= 30
       0 1316.34    15.1 1311.43      29  1304.6      32 1303.58    37.9 1302.39
    48.1  1301.2    58.5 1300.41      78 1299.93    91.7 1299.96   100.9 1298.97
   120.2 1298.56   123.8  1298.1   130.3 1295.41   132.9 1294.67   134.9 1294.64
   137.5 1294.69   139.91295.443   146.6 1298.64   151.2 1299.12   160.4 1298.24
   169.5 1295.97   183.3 1293.83   187.8 1293.75   196.7 1294.54   202.6 1297.35
   206.2 1298.42   212.6  1298.5   229.1 1297.41   233.6 1298.41   242.4 1302.49
#Mann= 3 ,-1,0
       0      .1       0   130.3    .045       0   139.9      .1       0
#XS Ineff= 2 , 0
                          149.36         1304.53
Permanent Ineff=
       F       F
Bank Sta=130.3,139.9
XS Rating Curve= 0 ,0
Exp/Cntr(USF)=0,0
Exp/Cntr=0.3,0.1

Type RM Length L Ch R = 1 ,5389    ,102.9,100.6,97.4
XS GIS Cut Line= 4
 2142598.8833258639585.2588587232142606.62217586639612.989738125
2142604.68746335639752.9339434822142611.78140924639791.628193811
#Sta/Elev= 30
       0  1319.1     4.1 1315.77    12.4 1310.18    19.7 1304.37    24.8 1300.04
    28.8 1297.01    34.6 1293.91      41 1291.51      49 1287.21      53 1285.53
      57 1284.56      61 1284.19      65 1284.46      73 1285.47      81 1283.92
      85 1284.05      89 1284.48      93 1285.51      97 1286.95     101 1287.58
     109 1288.07     129 1289.93     133 1289.98     141 1288.81   148.2  1288.5
   165.5 1289.88   177.1 1291.34   181.2 1292.15   192.6 1294.99   208.1 1297.31
#Mann= 3 ,-1,0
       0      .1       0      73    .045       0      93      .1       0
Bank Sta=73,93
XS Rating Curve= 0 ,0
Exp/Cntr(USF)=0,0
Exp/Cntr=0.3,0.1

Type RM Length L Ch R = 1 ,5289    ,117.7,118.3,118.3
XS GIS Cut Line= 2
 2142497.1203013639605.1725807522142534.77414335639813.554935664
#Sta/Elev= 30
       0 1330.12    12.2 1321.63    16.3 1318.28    20.3 1314.39    32.5 1301.39
    36.6 1297.38    40.7 1293.93    48.8 1287.79    52.8 1284.18    56.9 1281.12
    57.51280.965      61 1280.06      65 1279.84    69.1 1279.91    73.2 1280.98
    73.81281.389    77.2 1283.61    81.3 1284.47   105.7  1285.4   121.9 1286.76
   138.2 1287.32   146.3  1287.8   154.5 1287.55   158.5 1287.95   170.7 1290.46
   174.8 1291.96   184.7 1296.84   191.1 1299.19   195.1 1300.19   211.8 1303.15
#Mann= 3 ,-1,0
       0      .1       0    57.5    .045       0    73.8      .1       0
Bank Sta=57.5,73.8
XS Rating Curve= 0 ,0
Exp/Cntr(USF)=0,0
Exp/Cntr=0.3,0.1

Type RM Length L Ch R = 1 ,5171    ,165.1,162.8,158.7
XS GIS Cut Line= 3
2142386.06494899639643.3002342162142403.47736164639738.101147522
2142451.20027037639836.771485862
#Sta/Elev= 30
       0 1311.82       6 1305.92    10.3 1302.16    22.2 1292.77    26.3 1290.07
    30.4    1288    38.5 1284.82    46.6 1281.21    50.7 1279.14    54.8 1277.49
    58.8  1276.9      67 1276.67      71 1276.88    73.61277.495    85.9 1279.89
    91.4  1281.4    95.4 1281.67    99.2 1281.44   108.7    1280   113.1 1279.84
   120.2 1280.11   139.8 1281.38   153.1 1280.38   156.1  1280.5   170.9 1282.41
   175.3 1283.62   180.1 1285.63   188.7 1290.79     201 1298.83     206 1301.43
#Mann= 4 ,-1,0
       0      .1       0    54.8    .045       0    73.6      .1       0
  196.39     .06       0
Bank Sta=54.8,73.6
XS Rating Curve= 0 ,0
Exp/Cntr(USF)=0,0
Exp/Cntr=0.3,0.1

Type RM Length L Ch R = 1 ,5008    ,276.4,280.4,278.5
XS GIS Cut Line= 2
2142225.82459685 639690.769106532142312.01198126639908.943810799
#Sta/Elev= 30
       0 1316.79     2.6 1314.92     6.9 1311.08    11.2 1306.29    15.5 1302.21
    49.9 1273.16    54.2 1271.68    62.8 1271.32    80.7 1272.25      90 1272.19
    93.1 1272.52    97.2 1273.53   101.5 1273.74  116.671271.533     123 1270.95
   126.2 1271.53   127.3  1271.8   131.6 1274.08   135.9 1274.91   144.5 1275.08
   157.4 1276.56     166 1275.52   170.3 1275.42   178.9 1276.34   191.7 1276.72
     201 1278.03   204.1 1278.95   213.3 1282.97   222.6 1288.59   234.6 1296.97
#Mann= 4 ,-1,0
       0      .1       0  116.67    .045       0   126.2      .1       0
     150     .06       0
Bank Sta=116.67,126.2
XS Rating Curve= 0 ,0
Exp/Cntr(USF)=0,0
Exp/Cntr=0.3,0.1

Type RM Length L Ch R = 1 ,4727    ,78.1,80.5,82.7
XS GIS Cut Line= 3
2142019.67911614639727.1616196652142015.51476297639745.481217623
2142017.08188011 639925.69968853
#Sta/Elev= 30
       0 1285.68     6.2 1279.91    15.8  1270.3    18.5 1268.02    22.5 1265.81
    26.5 1264.76    34.5 1263.34    50.5 1264.35    54.5 1264.31    62.5 1263.65
    70.5 1263.52    74.5 1262.97    78.5 1262.39    82.5 1262.32   85.421263.006
    86.5 1263.26    90.5 1264.97    94.5 1265.97   102.6 1266.95   110.5 1267.55
   130.5 1269.99   138.5 1270.35   158.5  1269.7   166.5 1268.87   170.5 1268.94
   175.2 1269.71   182.5 1270.48   186.5 1271.19   194.5 1273.95     199 1275.89
#Mann= 5 ,-1,0
       0      .1       0    74.5    .045       0   85.42      .1       0
   98.79     .06       0  198.79      .1       0
Bank Sta=74.5,85.42
XS Rating Curve= 0 ,0
Exp/Cntr(USF)=0,0
Exp/Cntr=0.3,0.1

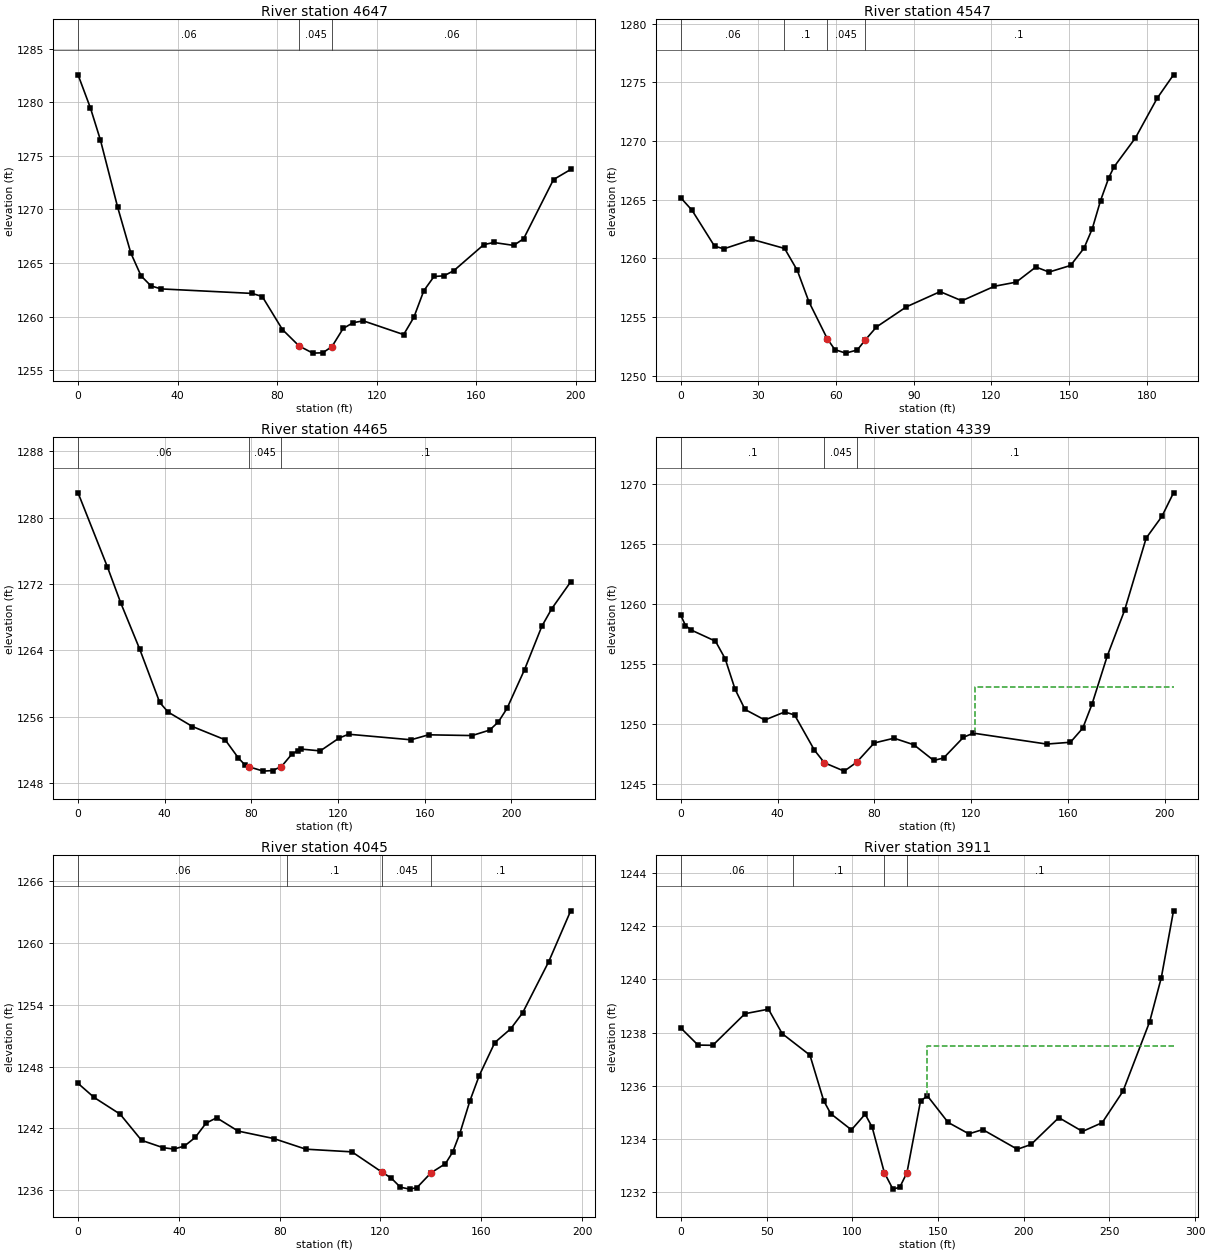
Type RM Length L Ch R = 1 ,4647    ,95.2,99.8,105
XS GIS Cut Line= 3
2141953.66699691639724.2613469612141929.66161023639863.871622122
2141930.92505163639920.094764608
#Sta/Elev= 30
       0 1282.56       5 1279.45       9 1276.47    15.9 1270.22    21.2 1265.94
    25.3 1263.81    29.3 1262.87    33.4 1262.59    69.9 1262.17      74 1261.88
    82.1  1258.8    88.81257.267    94.3  1256.6    98.3 1256.63     102 1257.21
   106.5  1258.9   110.5 1259.44   114.6 1259.61   130.8 1258.33   134.9 1259.94
   138.9 1262.42     143 1263.75     147 1263.81     151  1264.3     163 1266.72
     167 1266.92     175 1266.65     179 1267.27     191 1272.79   197.9 1273.73
#Mann= 3 ,-1,0
       0     .06       0    88.8    .045       0     102     .06       0
Bank Sta=88.8,102
XS Rating Curve= 0 ,0
Exp/Cntr(USF)=0,0
Exp/Cntr=0.3,0.1

Type RM Length L Ch R = 1 ,4547    ,83.9,82.4,80.4
XS GIS Cut Line= 4
2141884.03922532639719.0831002692141836.16694632639796.277506999
2141850.58577395639840.3625966172141835.01282813 639891.16643498
#Sta/Elev= 30
       0 1265.15     4.3  1264.1      13 1261.04    16.6 1260.81    27.6 1261.61
    40.1 1260.84      45 1258.97    49.5 1256.29    56.6 1253.14    59.5 1252.22
    63.7 1251.92    68.2 1252.19    71.1    1253    75.6 1254.15    87.2 1255.87
   100.2 1257.16   108.6 1256.38   121.2 1257.62   129.6 1257.97   137.2 1259.26
   142.3 1258.83   150.6 1259.39   155.8 1260.86     159 1262.52   162.2 1264.92
   165.4 1266.88   167.4 1267.79   175.7 1270.27   184.1 1273.65   190.4 1275.64
#Mann= 4 ,-1,0
       0     .06       0      40      .1       0    56.6    .045       0
    71.1      .1       0
Bank Sta=56.6,71.1
XS Rating Curve= 0 ,0
Exp/Cntr(USF)=0,0
Exp/Cntr=0.3,0.1

Type RM Length L Ch R = 1 ,4465    ,128.4,126,123.8
XS GIS Cut Line= 3
2141811.93753847639659.1603254892141757.78118497639780.253659585
2141768.66349443639874.368791776
#Sta/Elev= 30
       0 1283.01    13.5 1274.11    19.7 1269.74    28.5 1264.13    37.7 1257.72
    41.6 1256.56    52.8 1254.82    67.9 1253.22      74 1251.03      77  1250.2
    78.91249.963    85.5 1249.44    89.8 1249.51    93.91249.997    98.6 1251.46
   101.3  1251.9     103  1252.1   111.8 1251.88   120.5 1253.43   124.9 1253.89
   153.7 1253.22   161.8 1253.82   181.9 1253.73     190 1254.39     194 1255.37
     198    1257   206.1 1261.68   214.1 1266.92   218.7 1269.05   227.4 1272.27
#Mann= 3 ,-1,0
       0     .06       0    78.9    .045       0    93.9      .1       0
Bank Sta=78.9,93.9
XS Rating Curve= 0 ,0
Exp/Cntr(USF)=0,0
Exp/Cntr=0.3,0.1

Type RM Length L Ch R = 1 ,4339    ,281.5,294.1,305.8
XS GIS Cut Line= 3
2141675.43020886639627.3325913452141647.87030848639747.790925496
2141611.84207294639819.255972483
#Sta/Elev= 30
       0 1259.04     1.9  1258.2     4.3 1257.82    14.3 1256.89    18.3 1255.43
    22.4 1252.88    26.5 1251.19    34.7 1250.31    42.9 1250.98      47 1250.73
    55.2 1247.79    59.3 1246.74    67.5 1246.04    72.6 1246.77    79.9 1248.39
    88.1 1248.79    96.3 1248.24   104.5 1246.93   108.6 1247.14   116.8 1248.87
   120.9 1249.21   151.2  1248.3     161 1248.45   166.1 1249.63   169.9 1251.62
   176.2 1255.64   183.4 1259.48   192.3  1265.5   198.8 1267.31   203.6 1269.28
#Mann= 3 ,-1,0
       0      .1       0    59.3    .045       0    72.6      .1       0
#XS Ineff= 2 , 0
                          121.68         1253.03
Permanent Ineff=
       F       F
Bank Sta=59.3,72.6
XS Rating Curve= 0 ,0
Exp/Cntr(USF)=0,0
Exp/Cntr=0.3,0.1

Type RM Length L Ch R = 1 ,4045    ,123.7,133.7,141.3
XS GIS Cut Line= 3
2141480.71462575639557.5074783212141455.74542974639625.877423717
2141361.47674373639704.430120178
#Sta/Elev= 30
       0 1246.36     6.4 1244.99    16.7 1243.37    25.2 1240.83    33.7 1240.12
      38 1239.98    42.2 1240.27    46.5 1241.11    50.8  1242.5      55 1243.02
    63.5 1241.73    77.7    1241    90.4 1239.97   108.7 1239.71   120.71237.726
   124.3 1237.16   127.9 1236.28   131.6 1236.09   134.5 1236.24   140.1 1237.68
   145.8 1238.56   148.7  1239.7   151.5 1241.49   155.5 1244.66   159.2 1247.11
   165.4 1250.33   171.7 1251.66   176.4  1253.2   186.8 1258.19   195.5 1263.12
#Mann= 4 ,-1,0
       0     .06       0   82.79      .1       0   120.7    .045       0
   140.1      .1       0
Bank Sta=120.7,140.1
XS Rating Curve= 0 ,0
Exp/Cntr(USF)=0,0
Exp/Cntr=0.3,0.1

Type RM Length L Ch R = 1 ,3911    ,51.7,49.7,48.3
XS GIS Cut Line= 4
 2141438.4139604639579.7820785582141393.91110186639588.114290557
2141206.49261781639563.8442710392141158.79731019639587.303685396
#Sta/Elev= 30
       0 1238.17      10 1237.53    18.6 1237.52    37.4 1238.71    51.1 1238.88
    59.1 1237.96    75.3 1237.15    83.3 1235.44    87.4 1234.95    99.5 1234.34
   107.5 1234.93   111.6 1234.44   118.7 1232.73   123.7 1232.11   127.7 1232.18
   131.9 1232.73   139.8 1235.42   143.8 1235.62   155.9 1234.62     168 1234.19
   176.1 1234.35   196.3 1233.61   204.3 1233.79   220.5  1234.8   234.3 1234.28
   245.8 1234.61   257.9 1235.79   273.5 1238.41   280.3 1240.07   287.4 1242.58
#Mann= 4 ,-1,0
       0     .06       0   65.28      .1       0   118.7    .045       0
   131.9      .1       0
#XS Ineff= 2 , 0
                          143.48         1237.49
Permanent Ineff=
       F       F
Bank Sta=118.7,131.9
XS Rating Curve= 0 ,0
Exp/Cntr(USF)=0,0
Exp/Cntr=0.3,0.1

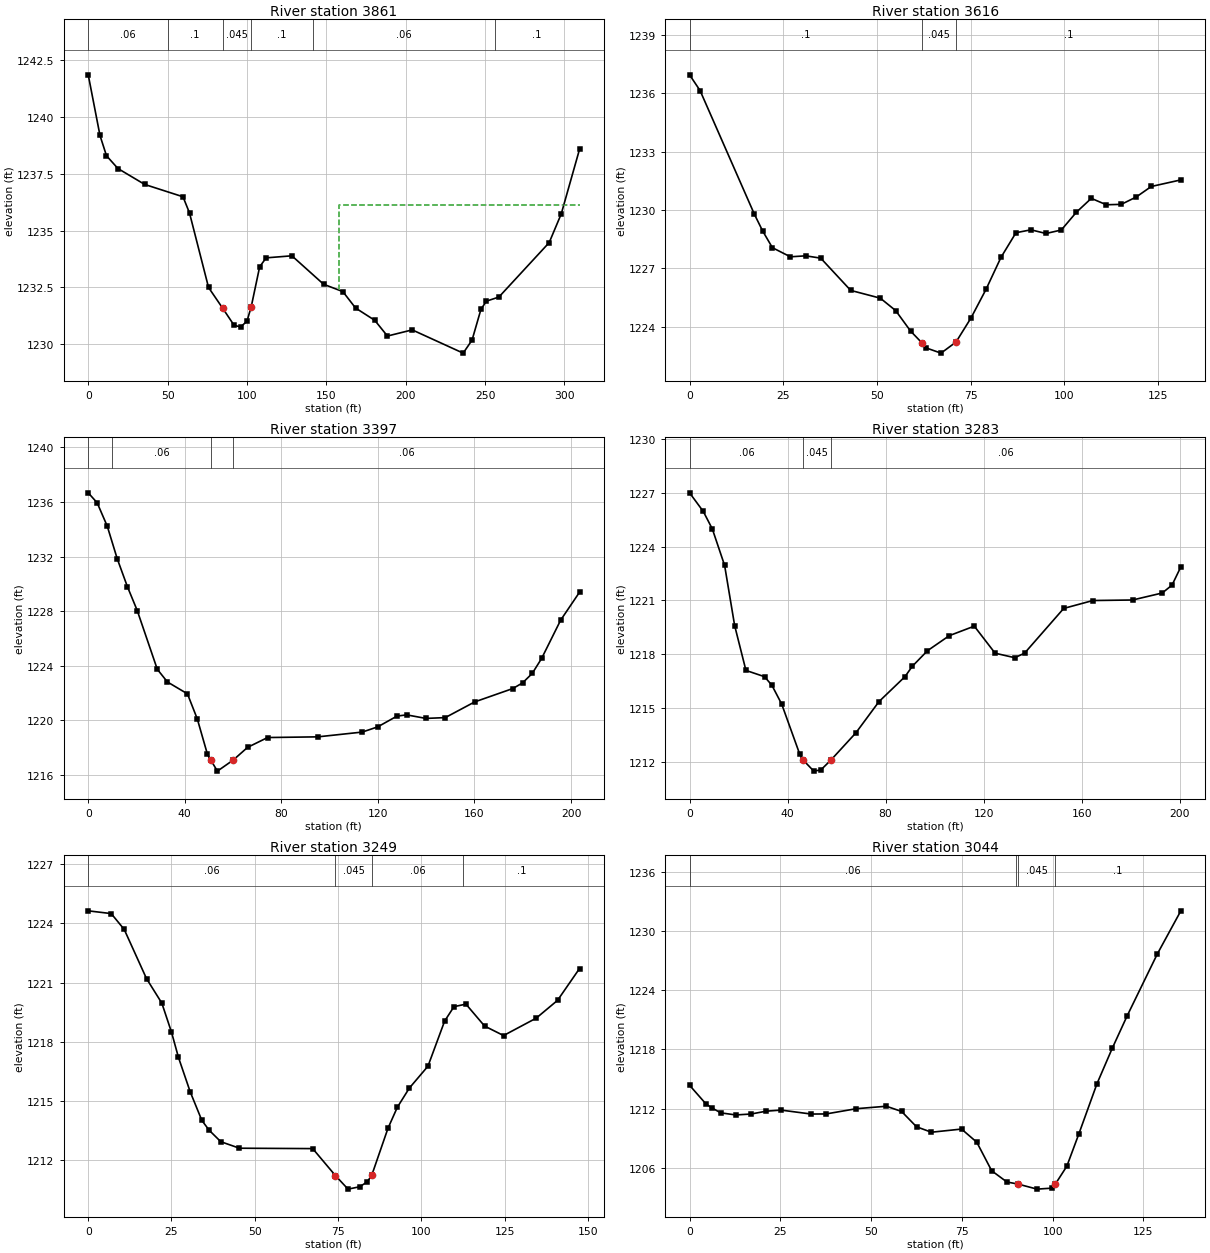
Type RM Length L Ch R = 1 ,3861    ,266.8,245,223.7
XS GIS Cut Line= 4
2141423.55644138639531.8939275292141372.36456793639537.525838952
2141188.98089143639517.0720263832141137.35760385639569.374916366
#Sta/Elev= 30
       0 1241.83     7.4 1239.17    11.5 1238.28    18.7 1237.72    35.6 1237.02
    59.7 1236.48    63.8 1235.77    75.8  1232.5    84.6  1231.6    91.9 1230.84
      96 1230.77     100 1231.02   102.7 1231.66     108 1233.41   112.1  1233.8
   128.3 1233.89   148.3 1232.64   160.4 1232.32   168.4  1231.6   180.5 1231.06
   188.5 1230.37   204.1 1230.64   236.2 1229.62   241.8 1230.19   247.4 1231.54
   250.8  1231.9   258.7 1232.08   290.4 1234.47     298 1235.73   309.5 1238.56
#Mann= 6 ,-1,0
       0     .06       0      50      .1       0    84.6    .045       0
   102.7      .1       0   141.5     .06       0  256.02      .1       0
#XS Ineff= 2 , 0
                          157.81          1236.1
Permanent Ineff=
       F       F
Bank Sta=84.6,102.7
XS Rating Curve= 0 ,0
Exp/Cntr(USF)=0,0
Exp/Cntr=0.3,0.1

Type RM Length L Ch R = 1 ,3616    ,215.9,218.9,218.5
XS GIS Cut Line= 4
2141156.90910433639414.8533062892141141.76030533639437.315318605
2141135.49183678639521.9396440742141134.61994226639541.065511375
#Sta/Elev= 30
       0 1236.96     2.8 1236.15    17.3 1229.78    19.5 1228.92    22.1 1228.06
    26.9 1227.59      31 1227.64      35 1227.52      43 1225.86    50.9 1225.46
      55 1224.82      59 1223.76    62.1 1223.14    63.1  1222.9    67.1 1222.63
    71.1  1223.2    75.1 1224.44    79.1 1225.91    83.1 1227.56    87.1 1228.83
    91.1 1228.98    95.1 1228.79    99.2 1228.97   103.2 1229.88   107.2  1230.6
   111.2 1230.27   115.2 1230.29   119.2 1230.67   123.2 1231.21   131.1 1231.55
#Mann= 3 ,-1,0
       0      .1       0    62.1    .045       0    71.1      .1       0
Bank Sta=62.1,71.1
XS Rating Curve= 0 ,0
Exp/Cntr(USF)=0,0
Exp/Cntr=0.3,0.1

Type RM Length L Ch R = 1 ,3397    ,125.2,113.9,102.8
XS GIS Cut Line= 3
2140968.49023081639325.6122183212140936.90419571639438.690223994
2140935.92388292639524.795042754
#Sta/Elev= 30
       0 1236.67     3.7 1235.94     7.9 1234.22      12 1231.85    16.2 1229.81
    20.3 1228.05    28.6 1223.75    32.8 1222.82    41.1 1221.95    45.2  1220.1
    49.4 1217.51    50.8 1217.09    53.5 1216.29   60.081217.104      66 1218.03
    74.3 1218.75    95.1  1218.8   113.5 1219.15   119.9 1219.53   127.9 1220.32
   131.9 1220.41   139.9 1220.15   147.9 1220.21   160.1 1221.36   175.9 1222.34
   179.9 1222.75   183.9 1223.44   187.8 1224.54   195.7 1227.35   203.5 1229.39
#Mann= 4 ,-1,0
       0      .1       0      10     .06       0    50.8    .045       0
   60.08     .06       0
Bank Sta=50.8,60.08
XS Rating Curve= 0 ,0
Exp/Cntr(USF)=0,0
Exp/Cntr=0.3,0.1

Type RM Length L Ch R = 1 ,3283    ,32.5,34,35.4
XS GIS Cut Line= 4
 2140821.1725751639340.0143834282140834.16177244639370.455544079
2140900.32600398639420.7532465592140906.70691256639504.813274522
#Sta/Elev= 30
       0    1227     5.6 1225.96     9.3 1224.98    14.3 1222.95    18.4 1219.59
      23 1217.09    30.6 1216.74    33.6 1216.26    37.6 1215.21      45  1212.4
   46.381212.084    50.7 1211.47    53.6 1211.54    57.7 1212.09    67.9 1213.61
    77.3 1215.35    87.9 1216.74    90.9 1217.32    97.1 1218.19     106 1219.03
   116.2 1219.56   124.7 1218.05   132.7  1217.8   136.7 1218.05   152.7 1220.55
   164.6 1220.99   180.8 1221.02   192.9 1221.41   196.9 1221.85   200.5 1222.87
#Mann= 3 ,-1,0
       0     .06       0   46.38    .045       0    57.7     .06       0
Bank Sta=46.38,57.7
XS Rating Curve= 0 ,0
Exp/Cntr(USF)=0,0
Exp/Cntr=0.3,0.1

Type RM Length L Ch R = 1 ,3249    ,191.7,205.7,217.8
XS GIS Cut Line= 3
2140774.22379983639351.9163934552140788.94399108639368.998829015
2140877.37325248639457.334922577
#Sta/Elev= 30
       0 1224.63     6.9 1224.49    10.8 1223.69    17.5  1221.2    22.1 1219.96
      25 1218.49    27.1 1217.21    30.6 1215.48    34.1 1214.03    36.3 1213.53
    39.8 1212.95    45.4 1212.62    67.4  1212.6   74.211211.236      78 1210.55
    81.5 1210.67    83.7 1210.91    85.1 1211.24      90 1213.63    92.8 1214.69
    96.4 1215.66     102 1216.77     107 1219.05   109.8 1219.78   113.4 1219.91
     119  1218.8   124.7 1218.32   134.5  1219.2   140.9  1220.1   147.5 1221.71
#Mann= 4 ,-1,0
       0     .06       0   74.21    .045       0    85.1     .06       0
  112.55      .1       0
Bank Sta=74.21,85.1
XS Rating Curve= 0 ,0
Exp/Cntr(USF)=0,0
Exp/Cntr=0.3,0.1

Type RM Length L Ch R = 1 ,3044    ,207.3,208.6,210.6
XS GIS Cut Line= 2
2140659.39045243639348.8549434452140623.98521338  639479.4480383
#Sta/Elev= 30
       0 1214.37     4.5 1212.49     6.1 1212.09     8.6 1211.58    12.7 1211.37
    16.9 1211.46    21.1 1211.75    25.2 1211.86    33.5 1211.46    37.6 1211.47
    45.9    1212    54.2 1212.25    58.4 1211.72    62.5 1210.17    66.6 1209.62
    74.9 1209.94    79.1 1208.61    83.2 1205.72    87.4 1204.58   90.391204.379
    95.7 1203.86    99.8 1203.96   100.7 1204.35   103.9 1206.18   107.2 1209.44
   112.2 1214.53   116.4 1218.11   120.5 1221.39   128.8 1227.65   135.3 1232.03
#Mann= 4 ,-1,0
       0     .06       0      90      .1       0   90.39    .045       0
   100.7      .1       0
Bank Sta=90.39,100.7
XS Rating Curve= 0 ,0
Exp/Cntr(USF)=0,0
Exp/Cntr=0.3,0.1

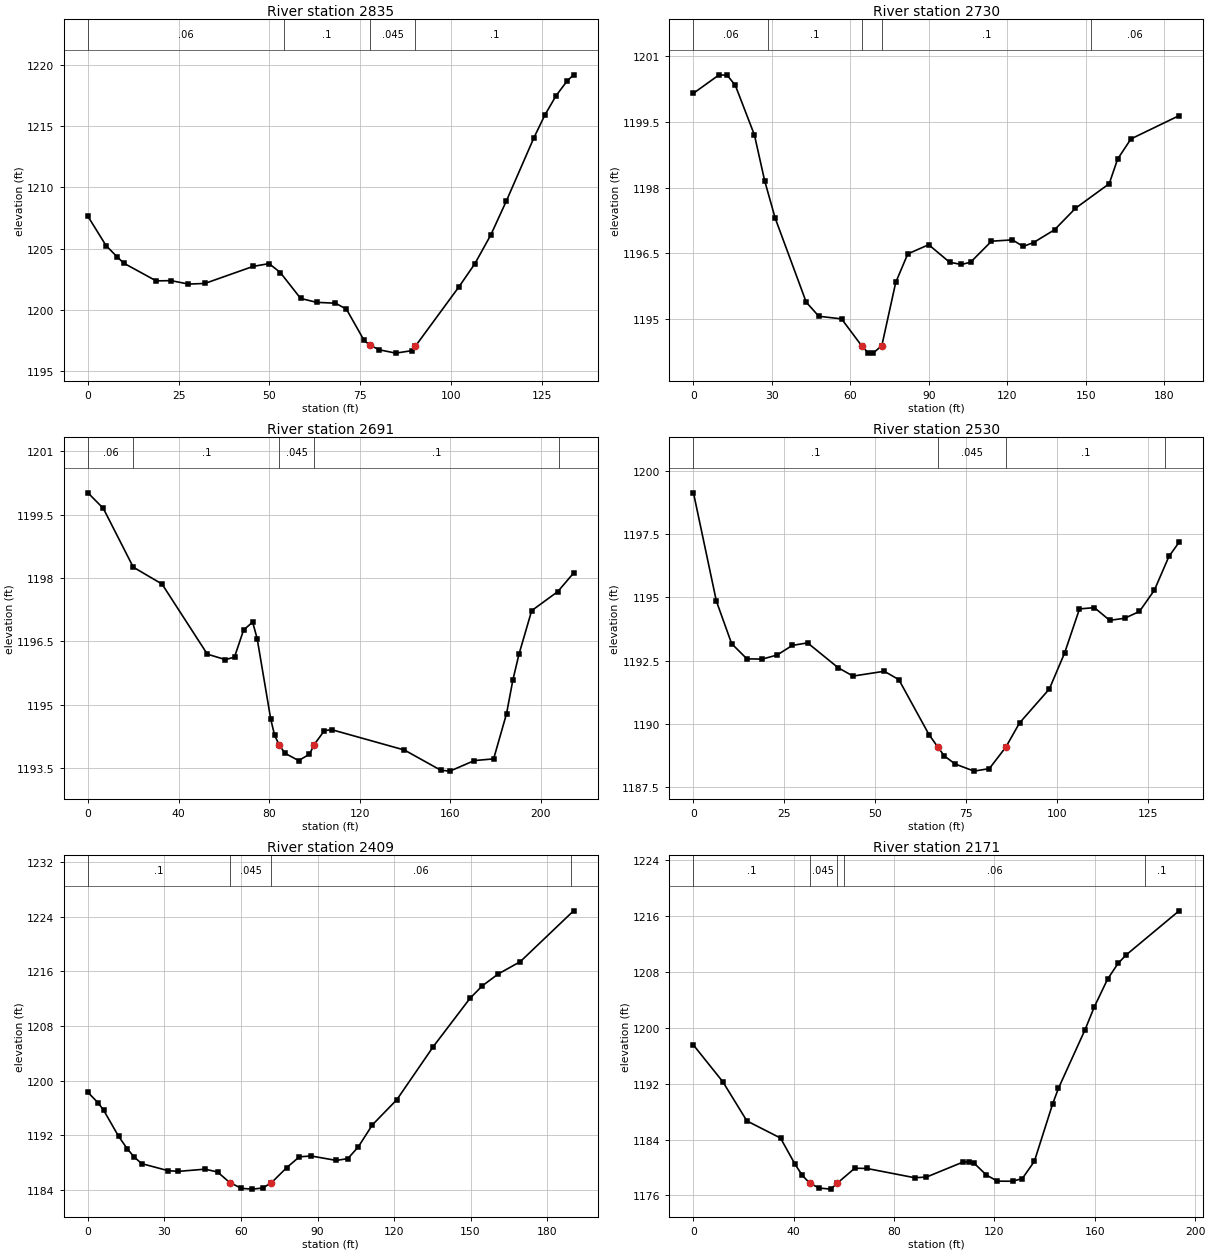
Type RM Length L Ch R = 1 ,2835    ,100.2,105.4,110.6
XS GIS Cut Line= 3
2140477.97177976639288.273057844 2140458.6246546639327.683868363
2140422.79664504639410.088290356
#Sta/Elev= 30
       0 1207.63       5 1205.24       8 1204.34     9.9 1203.81    18.8 1202.37
    22.9 1202.39    27.7 1202.11    32.2 1202.16    45.5 1203.55    49.9 1203.78
      53 1203.05    58.6 1200.94      63 1200.62    68.2 1200.55    71.2 1200.07
    76.1 1197.51    77.71197.123    80.3 1196.75    84.8 1196.48    89.2 1196.68
    90.2 1197.04   102.2 1201.88   106.6 1203.77     111 1206.12   115.3  1208.9
   122.9 1214.06   125.9  1215.9     129 1217.48     132 1218.66   133.8 1219.17
#Mann= 4 ,-1,0
       0     .06       0    53.9      .1       0    77.7    .045       0
    90.2      .1       0
Bank Sta=77.7,90.2
XS Rating Curve= 0 ,0
Exp/Cntr(USF)=0,0
Exp/Cntr=0.3,0.1

Type RM Length L Ch R = 1 ,2730    ,37.9,38.5,38.6
XS GIS Cut Line= 6
2140410.93556654639303.436344839 2140393.5545823639309.703754746
2140358.78417017639310.0515742912140336.16762492639327.633364897
2140259.24141021639331.7372640672140239.16911001639349.267568006
#Sta/Elev= 30
       0 1200.15     9.8 1200.57    12.9 1200.56      16 1200.33    23.3  1199.2
    27.2 1198.16    31.2 1197.31    43.1 1195.39    47.9 1195.07    56.6 1195.01
    64.31194.396    66.7 1194.24    68.7 1194.23      721194.403    77.3 1195.84
    81.9 1196.49    89.9  1196.7    97.9  1196.3   102.4 1196.25   105.9  1196.3
   113.9 1196.78   121.9 1196.81     126 1196.66     130 1196.75     138 1197.04
     146 1197.53   158.9 1198.09   162.1 1198.65   167.2 1199.11   185.6 1199.64
#Mann= 5 ,-1,0
       0     .06       0   28.48      .1       0    64.3    .045       0
      72      .1       0   151.9     .06       0
Bank Sta=64.3,72
XS Rating Curve= 0 ,0
Exp/Cntr(USF)=0,0
Exp/Cntr=0.3,0.1

Type RM Length L Ch R = 1 ,2691    ,166.9,161,135.1
XS GIS Cut Line= 6
2140402.97142516639275.2580743652140374.02273646639285.969389891
2140330.16306691639285.472595825 2140305.4910978639305.224098633
2140243.90128964639309.2974651172140211.39748906639342.393068742
#Sta/Elev= 30
       0 1200.02     6.8 1199.65      20 1198.26    32.7 1197.86    52.7  1196.2
    60.7 1196.07    64.7 1196.13    68.7 1196.77    72.7 1196.96    74.7 1196.57
    80.7 1194.66    82.4 1194.28    84.5 1194.04    87.1 1193.85      93 1193.68
    97.8 1193.83    99.9 1194.06   104.4 1194.39   107.7 1194.41   139.7 1193.93
   155.8 1193.45   159.8 1193.43   170.6 1193.68   179.1 1193.72   184.8 1194.79
   187.6 1195.59   190.3  1196.2   195.9 1197.23   207.4 1197.68   214.4 1198.12
#Mann= 5 ,-1,0
       0     .06       0      20      .1       0    84.5    .045       0
    99.9      .1       0  208.06     .06       0
Bank Sta=84.5,99.9
XS Rating Curve= 0 ,0
Exp/Cntr(USF)=0,0
Exp/Cntr=0.3,0.1

Type RM Length L Ch R = 1 ,2530    ,124.1,120.9,118.4
XS GIS Cut Line= 4
2140164.61020954639211.1536383922140182.54303621639269.745905358
2140197.53616824639326.3689817982140199.80692098639339.949618915
#Sta/Elev= 30
       0 1199.12     6.3 1194.85    10.5 1193.17    14.7 1192.57    18.9 1192.56
      23 1192.72    27.2  1193.1    31.4  1193.2    39.8 1192.22    43.9 1191.89
    52.5 1192.08    56.5 1191.75    64.8 1189.58    67.21189.095      69 1188.74
      72 1188.42    77.2 1188.14    81.4 1188.24   85.941189.088    89.7 1190.04
    97.9 1191.38   102.1  1192.8   106.2 1194.54   110.3 1194.59   114.5 1194.09
   118.6 1194.17   122.7 1194.44   126.8 1195.28   130.8 1196.61   133.6 1197.17
#Mann= 4 ,-1,0
       0      .1       0    67.2    .045       0   85.94      .1       0
  129.85     .06       0
Bank Sta=67.2,85.94
XS Rating Curve= 0 ,0
Exp/Cntr(USF)=0,0
Exp/Cntr=0.3,0.1

Type RM Length L Ch R = 1 ,2409    ,237.5,238.7,235.4
XS GIS Cut Line= 4
2140040.74951141 639275.246582042140074.01712504639324.037911253
2140076.51561594639334.0318748422140143.20730193639435.042289835
#Sta/Elev= 30
       0 1198.29     3.9 1196.79     6.1 1195.71      12 1191.87    15.4 1190.04
    18.2  1188.8    21.1 1187.86    31.4 1186.83    35.5 1186.73    45.9 1187.05
    50.8 1186.64    55.6 1185.09    60.2 1184.24    64.4 1184.13    68.5 1184.29
   71.951185.069    77.9 1187.27    82.9 1188.86    87.5 1188.98    97.4 1188.33
   101.9  1188.6     106 1190.32   111.5 1193.53   121.1 1197.22   135.4 1204.99
   149.8 1212.06   154.6 1213.88   160.9 1215.63   169.5 1217.42   190.4 1224.86
#Mann= 4 ,-1,0
       0      .1       0    55.6    .045       0   71.95     .06       0
  189.36      .1       0
Bank Sta=55.6,71.95
XS Rating Curve= 0 ,0
Exp/Cntr(USF)=0,0
Exp/Cntr=0.3,0.1

Type RM Length L Ch R = 1 ,2171    ,260.7,262.6,265.4
XS GIS Cut Line= 2
2139833.96691848639379.3384467112139939.74732531 639541.53507052
#Sta/Elev= 30
       0 1197.52    11.7 1192.27    21.3 1186.66    34.7 1184.21    40.5 1180.46
    43.4 1178.86    46.3 1177.78      50 1177.06    54.7  1176.9    57.3 1177.74
    64.3 1179.89    69.1 1179.86    88.2 1178.53    92.9 1178.63   107.3 1180.75
   109.9  1180.8     112 1180.57   116.8 1178.91   121.2 1178.04   127.2 1178.03
   131.1 1178.41   135.9 1180.88   143.2 1189.11   145.5 1191.33   156.1 1199.71
   159.8 1202.98   165.1 1206.96   169.3 1209.22   172.5 1210.42   193.6 1216.73
#Mann= 5 ,-1,0
       0      .1       0    46.3    .045       0    57.3      .1       0
      60     .06       0     180      .1       0
Bank Sta=46.3,57.3
XS Rating Curve= 0 ,0
Exp/Cntr(USF)=0,0
Exp/Cntr=0.3,0.1

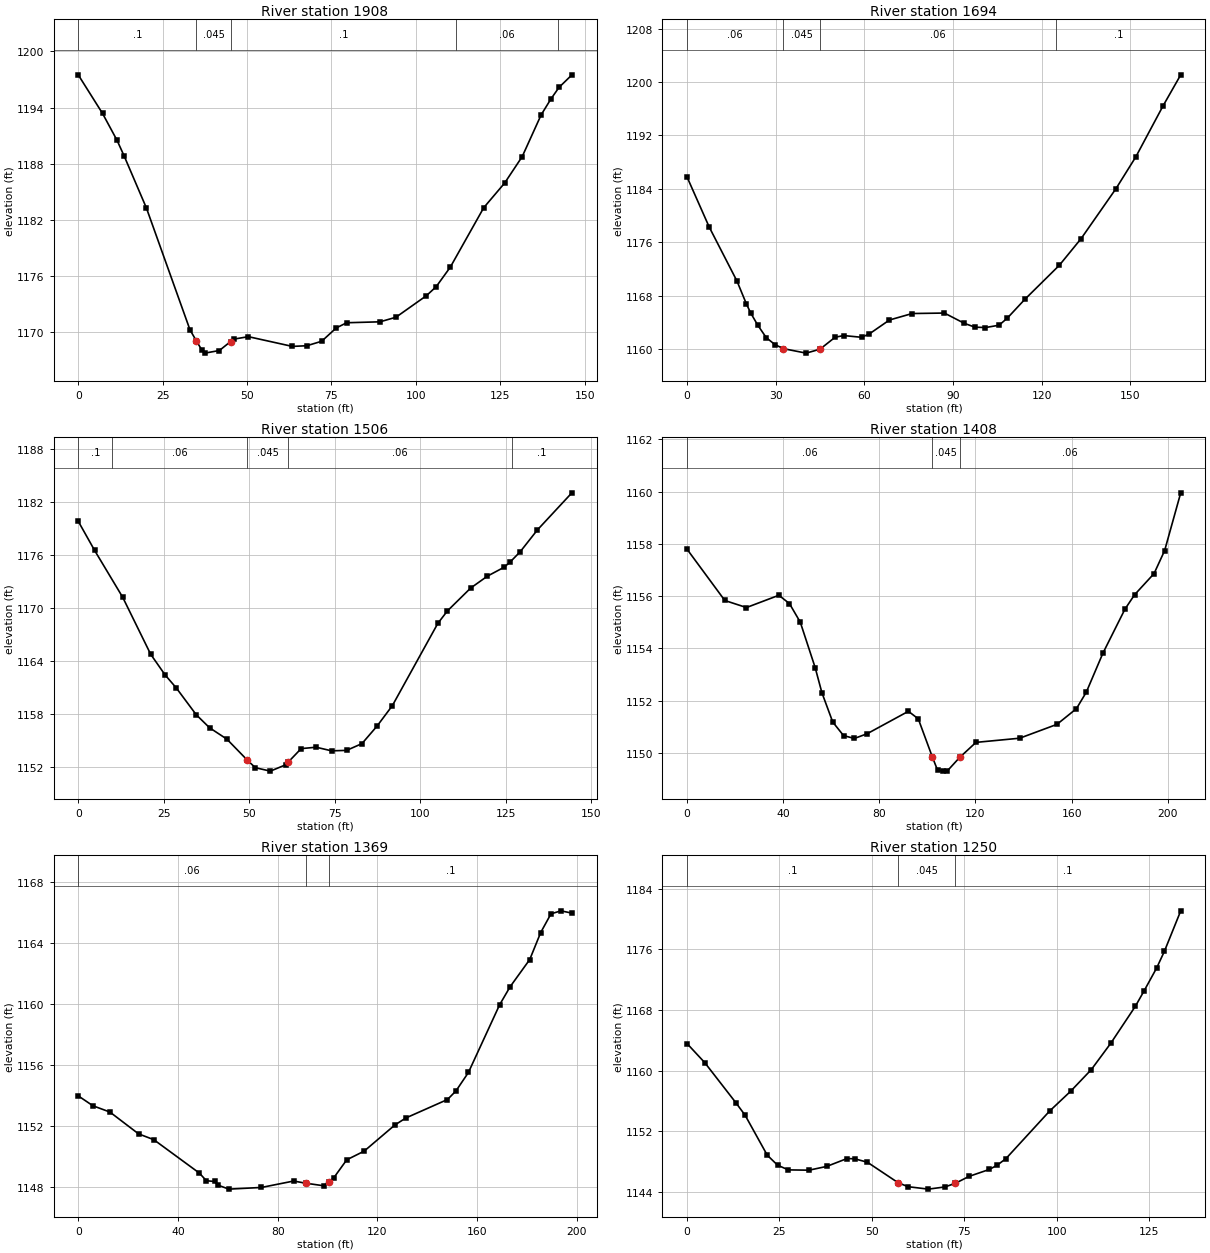
Type RM Length L Ch R = 1 ,1908    ,215.6,214.1,213
XS GIS Cut Line= 3
2139635.00381659639526.5436060342139670.02588134639611.628201308
2139706.16289037639651.975202823
#Sta/Elev= 30
       0  1197.5     7.2 1193.37    11.5 1190.49    13.6 1188.82    20.2 1183.25
    33.1 1170.22      35 1169.03    36.6 1168.07    37.5 1167.73    41.8 1168.01
    45.1 1168.96    46.1 1169.23    50.4 1169.49    63.4 1168.45    67.7 1168.52
    72.1    1169    76.4 1170.42    79.5 1170.98    89.4 1171.08    94.1 1171.57
   103.1 1173.87     106 1174.83   110.2 1176.93   120.1 1183.29   126.3 1185.93
   131.5 1188.76   137.1 1193.22     140 1194.92   142.4 1196.16   146.2 1197.49
#Mann= 5 ,-1,0
       0      .1       0      35    .045       0    45.1      .1       0
  112.01     .06       0  142.01      .1       0
Bank Sta=35,45.1
XS Rating Curve= 0 ,0
Exp/Cntr(USF)=0,0
Exp/Cntr=0.3,0.1

Type RM Length L Ch R = 1 ,1694    ,186.5,188.1,188.5
XS GIS Cut Line= 3
2139445.64920366639630.8192150772139484.96663528639694.710041456
2139531.16461743639774.327840483
#Sta/Elev= 30
       0 1185.76     7.5 1178.27    16.9 1170.18    20.1 1166.74    21.6 1165.36
    23.9  1163.6    26.8 1161.72    29.7 1160.69    32.6 1160.07    40.3  1159.4
      45 1159.99    50.1 1161.78      53 1162.03    59.1 1161.77    61.7 1162.28
    68.5 1164.36    76.2 1165.33    87.1  1165.4    93.8 1163.87    97.4 1163.29
     101 1163.23   105.6 1163.58   108.4 1164.64   114.3 1167.44     126 1172.55
   133.4 1176.56   145.2 1184.04   151.9 1188.79   161.1 1196.41   167.1 1201.07
#Mann= 4 ,-1,0
       0     .06       0    32.6    .045       0      45     .06       0
  125.02      .1       0
Bank Sta=32.6,45
XS Rating Curve= 0 ,0
Exp/Cntr(USF)=0,0
Exp/Cntr=0.3,0.1

Type RM Length L Ch R = 1 ,1506    ,107.3,97.7,85.4
XS GIS Cut Line= 4
2139294.66011463639716.4769227572139301.10915636639744.422770216
2139335.50404554639814.6456689582139357.00085127639845.457757181
#Sta/Elev= 30
       0 1179.83     4.8 1176.52      13 1171.22    21.2 1164.75    25.4 1162.42
    28.7 1160.93    34.5 1157.91    38.4 1156.43    43.5 1155.13    49.5 1152.74
    51.8  1151.9    56.2 1151.51    60.7 1152.23    61.4 1152.52    65.2 1154.06
    69.6 1154.22    74.1 1153.81    78.5 1153.86      83 1154.63    87.4 1156.61
    91.9 1158.94   105.2 1168.26     108 1169.67   114.8 1172.26   119.7 1173.61
   124.6 1174.62   126.4 1175.23   129.3 1176.38   134.3 1178.84   144.4 1183.05
#Mann= 5 ,-1,0
       0      .1       0      10     .06       0    49.5    .045       0
    61.4     .06       0  126.87      .1       0
Bank Sta=49.5,61.4
XS Rating Curve= 0 ,0
Exp/Cntr(USF)=0,0
Exp/Cntr=0.3,0.1

Type RM Length L Ch R = 1 ,1408    ,41.8,39.5,40.7
XS GIS Cut Line= 5
2139134.22013714639860.0250689222139216.57221619639817.823551337
2139247.73876964639820.5389855782139277.96315052639810.197708891
2139327.23234599639803.953101792
#Sta/Elev= 30
       0 1157.79    15.7 1155.83    24.7 1155.56    38.2 1156.03    42.6 1155.71
    47.1    1155    53.3 1153.26    56.1  1152.3    60.6 1151.18    65.1 1150.66
    69.6 1150.55    74.9 1150.73    92.1 1151.59    96.2  1151.3     1021149.854
   104.2 1149.34   106.3  1149.3   108.2  1149.3   113.41149.822   120.2  1150.4
   138.4 1150.56   153.9 1151.09     162 1151.69   166.1 1152.32     173 1153.81
   182.2  1155.5   186.2 1156.05   194.3 1156.86   198.7 1157.74   205.4 1159.95
#Mann= 3 ,-1,0
       0     .06       0     102    .045       0   113.4     .06       0
Bank Sta=102,113.4
XS Rating Curve= 0 ,0
Exp/Cntr(USF)=0,0
Exp/Cntr=0.3,0.1

Type RM Length L Ch R = 1 ,1369    ,107.7,118.3,124.4
XS GIS Cut Line= 5
2139124.49143525639889.1684174412139202.90096739639856.040963702
2139225.24248491639854.5276640232139295.61482009639833.571274211
2139312.53459297639831.117755331
#Sta/Elev= 30
       0    1154     5.9 1153.35    12.7 1152.94    24.2 1151.51    30.3 1151.13
    48.6 1148.94    51.4 1148.44    54.7 1148.39    56.1 1148.15    60.4 1147.89
    73.5    1148    86.4 1148.42    91.2 1148.28    98.4 1148.11   100.6 1148.38
   102.4 1148.61   107.7 1149.81   114.7 1150.38     127 1152.09   131.4 1152.55
   148.1 1153.76   151.5 1154.32   156.5 1155.53     169 1159.96   173.2 1161.14
   181.1 1162.93   185.5  1164.7   189.6 1165.92   193.6 1166.12     198 1165.97
#Mann= 3 ,-1,0
       0     .06       0    91.2    .045       0   100.6      .1       0
Bank Sta=91.2,100.6
XS Rating Curve= 0 ,0
Exp/Cntr(USF)=0,0
Exp/Cntr=0.3,0.1

Type RM Length L Ch R = 1 ,1250    ,218.6,223.7,231.2
XS GIS Cut Line= 3
2139096.82566207639901.853561508 2139128.8136571639932.318318675
2139193.93207554639993.628642475
#Sta/Elev= 30
       0 1163.57     4.8 1161.05    13.2 1155.77    15.7 1154.12    21.7 1148.84
    24.5 1147.52    27.4  1146.9      33 1146.86    37.8 1147.36    43.3  1148.4
    45.4 1148.36    48.8 1147.91    57.1 1145.21    59.8 1144.68    65.3 1144.36
    69.8 1144.65    72.6 1145.13    76.3 1146.04    81.8 1146.96    83.9 1147.51
    86.3 1148.39    98.1 1154.66   103.8 1157.28   109.4 1160.14   114.7 1163.64
   121.3 1168.48   123.6 1170.46   127.1 1173.57   129.2 1175.78   133.6  1181.1
#Mann= 3 ,-1,0
       0      .1       0    57.1    .045       0    72.6      .1       0
Bank Sta=57.1,72.6
XS Rating Curve= 0 ,0
Exp/Cntr(USF)=0,0
Exp/Cntr=0.3,0.1