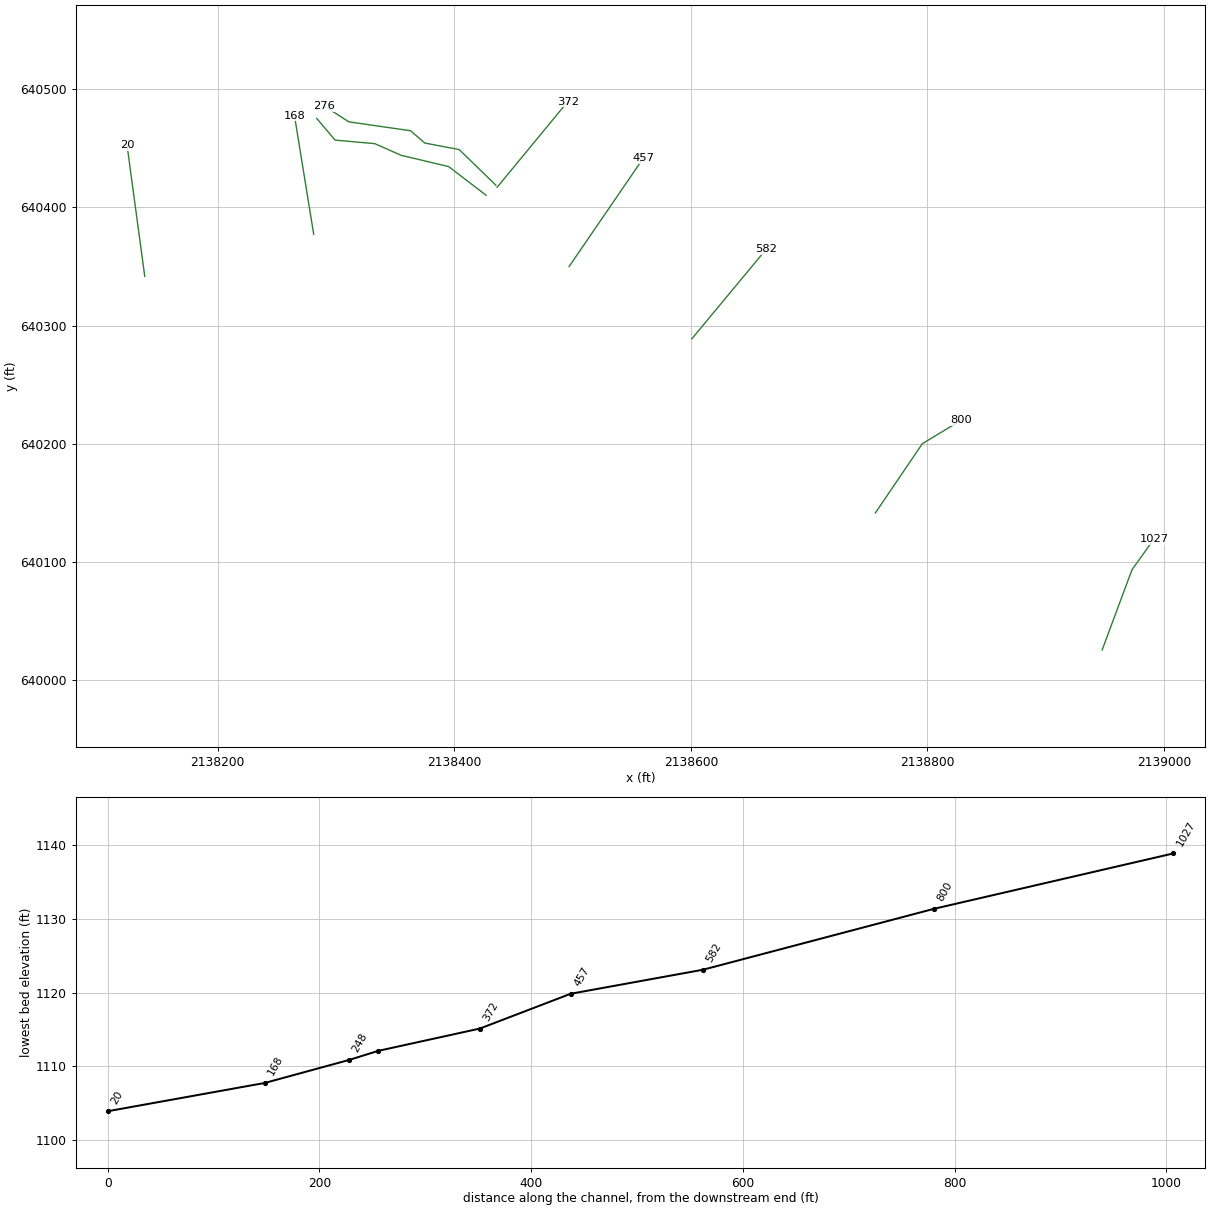
HEC-RAS study TRACERN.prj: TRACERN

--- TRACERN.g01 (geometry) --- (continued)

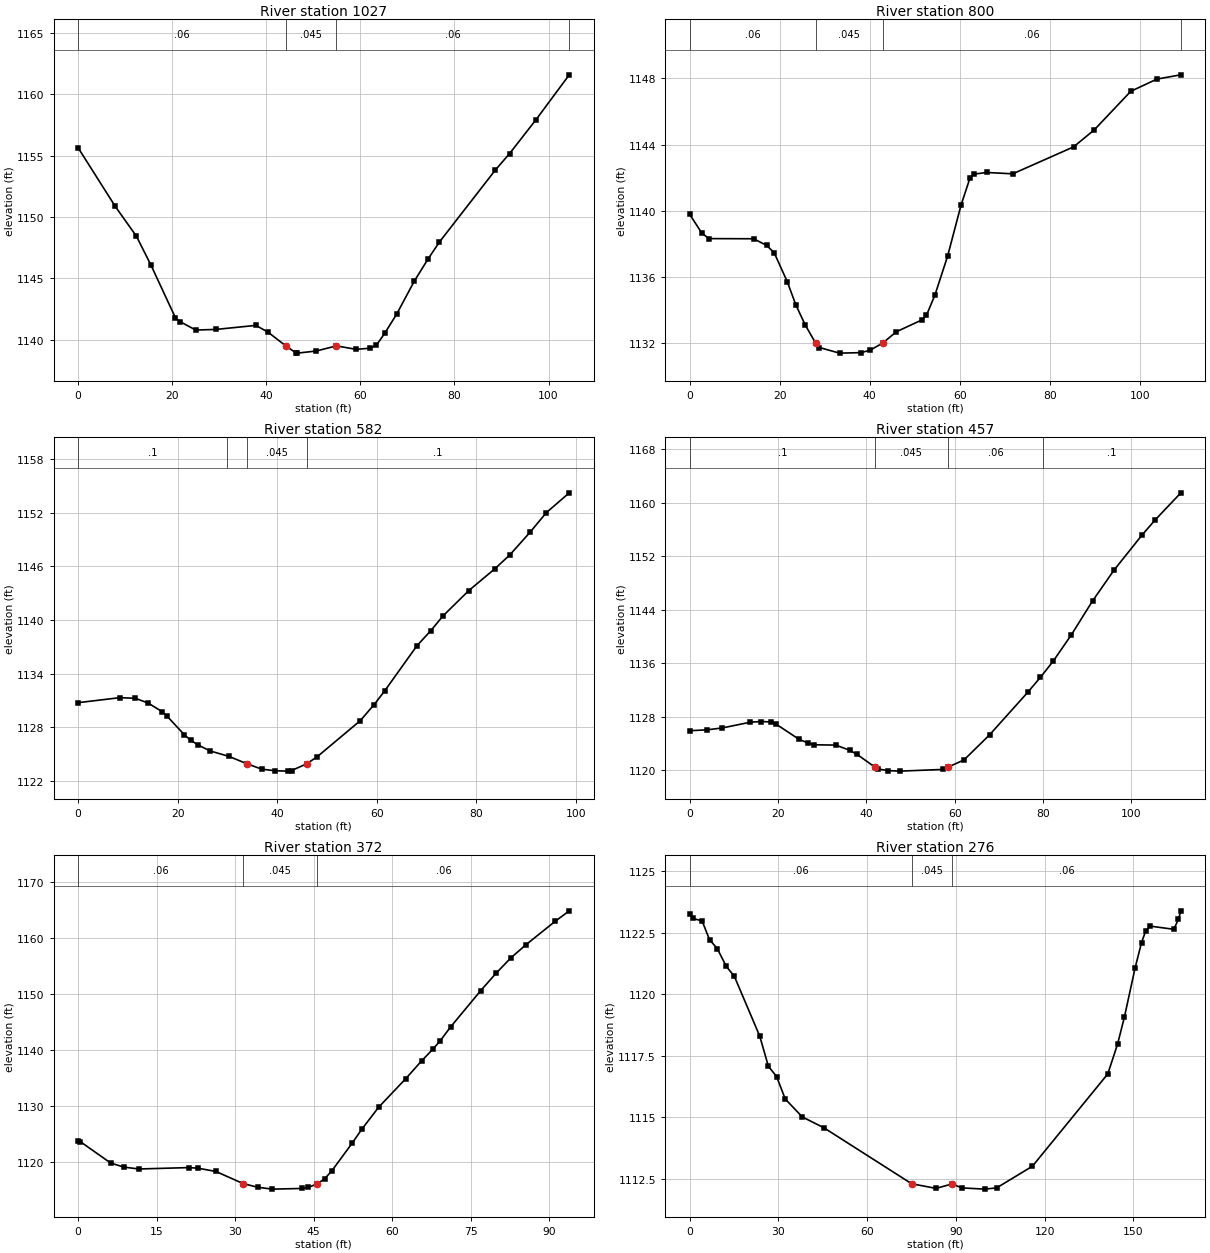
Type RM Length L Ch R = 1 ,1027    ,228.7,226.3,214.1
XS GIS Cut Line= 3
2138947.70315089640025.7509370972138972.94083748640093.611699744
2138991.59559185640119.609132834
#Sta/Elev= 27
       0 1155.64     7.9 1150.86    12.4 1148.43    15.5 1146.07    20.7 1141.78
    21.7 1141.47      25 1140.79    29.3 1140.84    37.8 1141.17    40.4 1140.61
   44.171139.491    46.3 1138.93    46.6 1138.91    50.6 1139.08    54.9  1139.5
    59.1 1139.22    62.1 1139.31    63.4 1139.55    65.2 1140.54    67.7 1142.08
    71.5  1144.8    74.4 1146.59    76.8 1147.96    88.7 1153.83    91.7 1155.16
    97.3 1157.91   104.4 1161.58
#Mann= 4 ,-1,0
       0     .06       0   44.17    .045       0    54.9     .06       0
   104.4      .1       0
Bank Sta=44.17,54.9
XS Rating Curve= 0 ,0
Exp/Cntr(USF)=0,0
Exp/Cntr=0.3,0.1

Type RM Length L Ch R = 1 ,800     ,218.3,218.1,214.8
XS GIS Cut Line= 3
2138756.01558267640141.6461279682138795.71588351640200.151834462
2138828.62534341 640220.00198488
#Sta/Elev= 30
       0 1139.78     2.7 1138.64     4.3 1138.31    14.2  1138.3    17.1  1137.9
    18.8 1137.44    21.7 1135.69    23.6 1134.29    25.7 1133.07   27.981131.989
    28.8 1131.72    33.3 1131.38    38.1 1131.41    40.1 1131.56    42.9 1131.99
    45.9 1132.67    51.6 1133.39    52.6 1133.66    54.5  1134.9    57.3 1137.24
    60.3 1140.34    62.3 1141.99    63.1 1142.21      66 1142.31    71.8 1142.23
    85.3 1143.86    89.9 1144.89      98 1147.22   103.8 1147.96   109.1 1148.22
#Mann= 4 ,-1,0
       0     .06       0   27.98    .045       0    42.9     .06       0
  109.14      .1       0
Bank Sta=27.98,42.9
XS Rating Curve= 0 ,0
Exp/Cntr(USF)=0,0
Exp/Cntr=0.3,0.1

Type RM Length L Ch R = 1 ,582     ,123.5,124.9,125.9
XS GIS Cut Line= 2
2138600.80258809640288.7562496282138663.85988492640364.711629899
#Sta/Elev= 30
       0 1130.76     8.4 1131.32    11.5 1131.25    14.1 1130.71    16.9 1129.75
    17.8  1129.3    21.3  1127.2    22.6 1126.57    24.1 1126.04    26.5 1125.37
    30.3 1124.76    33.9 1123.94    36.9 1123.33    39.6 1123.15    42.1 1123.11
    42.9 1123.18    45.91123.917    48.1 1124.74    56.7 1128.75    59.5 1130.55
    61.6 1132.07    68.1 1137.13    70.9 1138.82    73.3 1140.44    78.5 1143.28
    83.7  1145.7    86.7 1147.24    90.8 1149.79    94.1    1152    98.7 1154.21
#Mann= 4 ,-1,0
       0      .1       0      30     .06       0    33.9    .045       0
    45.9      .1       0
Bank Sta=33.9,45.9
XS Rating Curve= 0 ,0
Exp/Cntr(USF)=0,0
Exp/Cntr=0.3,0.1

Type RM Length L Ch R = 1 ,457     ,87.1,85.9,84.6
XS GIS Cut Line= 2
2138497.09301623640349.9084874862138559.90634418640441.644010592
#Sta/Elev= 30
       0 1125.89       4 1126.03     7.4 1126.31    13.7 1127.16    16.1 1127.27
    18.5  1127.2    19.6 1126.86    24.7 1124.63    26.7 1124.07    28.2 1123.79
    33.1 1123.74    36.2 1122.97    37.9 1122.35      42 1120.42    42.7 1120.16
    44.9 1119.93    47.6 1119.85    57.3  1120.1    58.41120.425    62.1 1121.52
    67.9 1125.28    76.5 1131.61    79.4 1133.87    82.3 1136.29    86.4 1140.22
    91.2 1145.29    96.1 1149.93   102.4 1155.14   105.3 1157.35   111.2 1161.46
#Mann= 4 ,-1,0
       0      .1       0      42    .045       0    58.4     .06       0
      80      .1       0
Bank Sta=42,58.4
XS Rating Curve= 0 ,0
Exp/Cntr(USF)=0,0
Exp/Cntr=0.3,0.1

Type RM Length L Ch R = 1 ,372     ,73.6,96,118.7
XS GIS Cut Line= 2
2138436.19992053640416.8607220342138495.86006998640489.214520307
#Sta/Elev= 30
       0 1123.77      .4 1123.62     6.2  1119.8     8.7 1119.06    11.6 1118.72
    21.2 1118.97    22.9 1118.86    26.3 1118.28    31.5 1116.12    34.3 1115.45
    37.1 1115.12    42.8 1115.24      44 1115.44    45.7 1116.08    47.1 1116.98
    48.5 1118.44    52.3 1123.29    54.2 1125.85    57.4 1129.76    62.6 1134.89
    65.6 1138.04    67.8 1140.18    69.1 1141.57    71.2 1144.18    76.9 1150.61
    79.8 1153.68    82.6 1156.41    85.5 1158.78    91.1 1162.98    93.8 1164.86
#Mann= 3 ,-1,0
       0     .06       0    31.5    .045       0    45.7     .06       0
Bank Sta=31.5,45.7
XS Rating Curve= 0 ,0
Exp/Cntr(USF)=0,0
Exp/Cntr=0.3,0.1

Type RM Length L Ch R = 1 ,276     ,31.5,27.4,23.7
XS GIS Cut Line= 6
2138435.17132336640418.6714127052138404.16944651640448.766940738
2138375.06362243640454.3081443862138363.06991867640464.696993906
2138310.91588972640472.2154948372138290.15991019640485.583117423
#Sta/Elev= 30
       0 1123.27     1.1 1123.08     4.2 1122.98     6.7 1122.22     9.3 1121.86
    12.4 1121.13    15.1 1120.73    23.7  1118.3    26.6 1117.08    29.4 1116.66
    32.3 1115.75    38.1 1115.02    45.4 1114.58   75.071112.308    83.3 1112.12
    88.7  1112.3    92.1 1112.14    99.7 1112.09   103.8 1112.14   115.9 1113.02
   141.4 1116.77   144.7 1117.98     147 1119.07   150.6 1121.06   152.8  1122.1
   154.2 1122.57   155.7 1122.77   163.7 1122.64   165.3 1123.05   166.1 1123.39
#Mann= 3 ,-1,0
       0     .06       0   75.07    .045       0    88.7     .06       0
Bank Sta=75.07,88.7
XS Rating Curve= 0 ,0
Exp/Cntr(USF)=0,0
Exp/Cntr=0.3,0.1

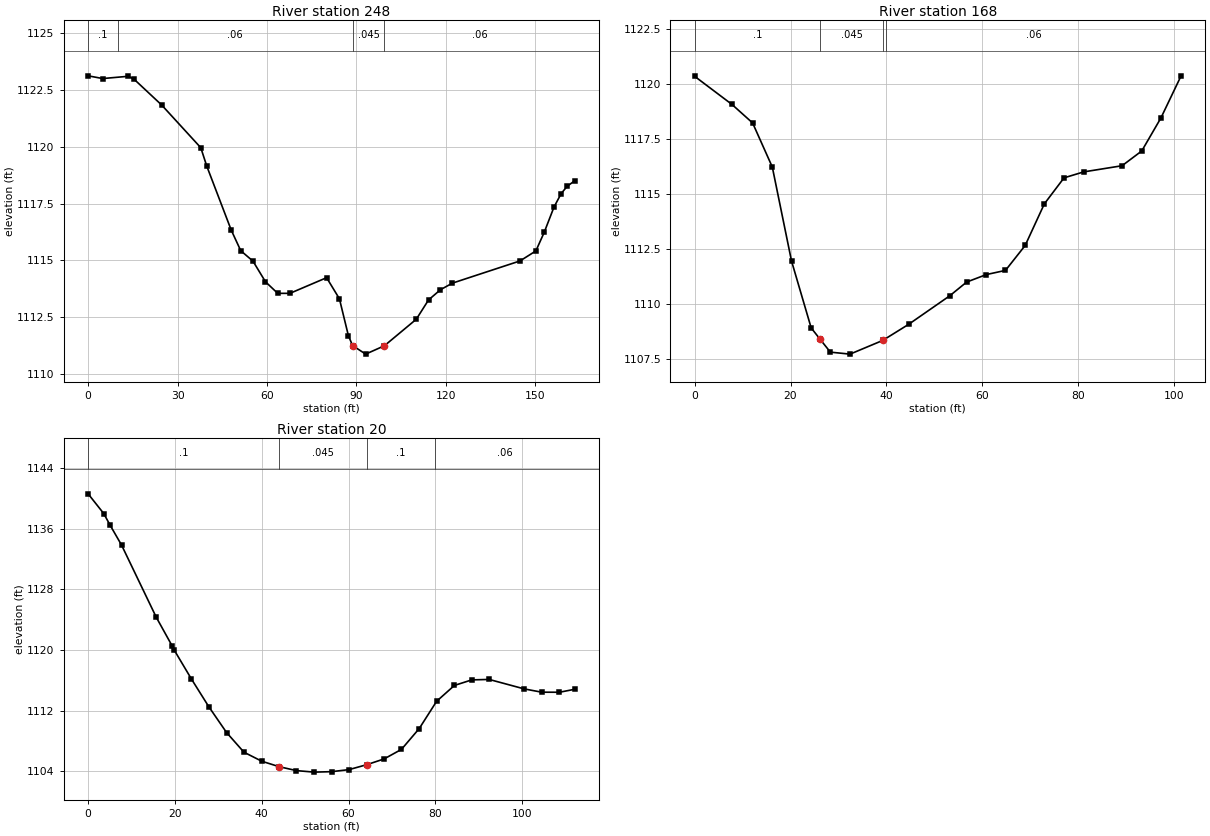
Type RM Length L Ch R = 1 ,248     ,90.8,79.8,67.6
XS GIS Cut Line= 6
2138426.89056582640410.1723392692138395.27177763 640434.39770055
2138355.07563834640443.9365765572138332.83704967 640453.77334077
2138299.26267368640456.7841363172138283.72597169640475.116045335
#Sta/Elev= 30
       0 1123.13     4.9 1123.01    13.5 1123.11    15.5 1122.97    24.7 1121.84
    37.8 1119.96    39.8 1119.15      48 1116.33    51.2 1115.42    55.3 1114.96
    59.5 1114.05    63.6 1113.54    67.7 1113.54      80 1114.23    84.3  1113.3
    87.3 1111.68    88.7 1111.24    93.1 1110.86    99.4 1111.23   110.1  1112.4
   114.2 1113.25   118.2  1113.7   122.2 1113.99   144.9 1114.97   150.2 1115.41
     153 1116.23   156.3 1117.35   158.7 1117.94   160.7 1118.26   163.2  1118.5
#Mann= 4 ,-1,0
       0      .1       0      10     .06       0    88.7    .045       0
    99.4     .06       0
Bank Sta=88.7,99.4
XS Rating Curve= 0 ,0
Exp/Cntr(USF)=0,0
Exp/Cntr=0.3,0.1

Type RM Length L Ch R = 1 ,168     ,105.2,148.4,104.3
XS GIS Cut Line= 2
2138281.16833345640377.2001209282138264.95028545640477.311049802
#Sta/Elev= 23
       0 1120.34     7.8 1119.06    12.1 1118.22    16.2 1116.22    20.2 1111.96
    24.3 1108.92    26.21108.394    28.3 1107.82    32.4 1107.73    39.2 1108.35
    44.6 1109.08    53.2 1110.38    56.7    1111    60.8 1111.34    64.8 1111.53
    68.9 1112.66    72.9 1114.55      77 1115.73    81.1    1116    89.1 1116.28
    93.2 1116.95    97.2 1118.45   101.4 1120.36
#Mann= 4 ,-1,0
       0      .1       0    26.2    .045       0    39.2      .1       0
      40     .06       0
Bank Sta=26.2,39.2
XS Rating Curve= 0 ,0
Exp/Cntr(USF)=0,0
Exp/Cntr=0.3,0.1

Type RM Length L Ch R = 1 ,20      ,,,
XS GIS Cut Line= 2
2138138.34538065640341.5837827522138123.35965234640452.628958336
#Sta/Elev= 29
       0 1140.58     3.6 1137.98     5.1 1136.41     7.7 1133.83    15.7 1124.31
    19.4 1120.49    19.8 1120.02    23.8 1116.17    27.8 1112.52    31.9 1109.11
    35.9 1106.52      40 1105.33      44 1104.61      48 1104.09    52.1 1103.89
    56.1 1103.95    60.1 1104.22    64.2 1104.87    68.2 1105.63    72.2 1106.89
    76.3 1109.64    80.3 1113.23    84.4 1115.32    88.4 1116.05    92.4 1116.11
   100.5 1114.86   104.5 1114.43   108.6 1114.42   112.1 1114.81
#Mann= 4 ,-1,0
       0      .1       0      44    .045       0    64.2      .1       0
      80     .06       0
Bank Sta=44,64.2
XS Rating Curve= 0 ,0
Exp/Cntr(USF)=0,0
Exp/Cntr=0.3,0.1
LCMann Table=0

Chan Stop Cuts=-1
Use User Specified Reach Order=0
Composite Channel Slope=5